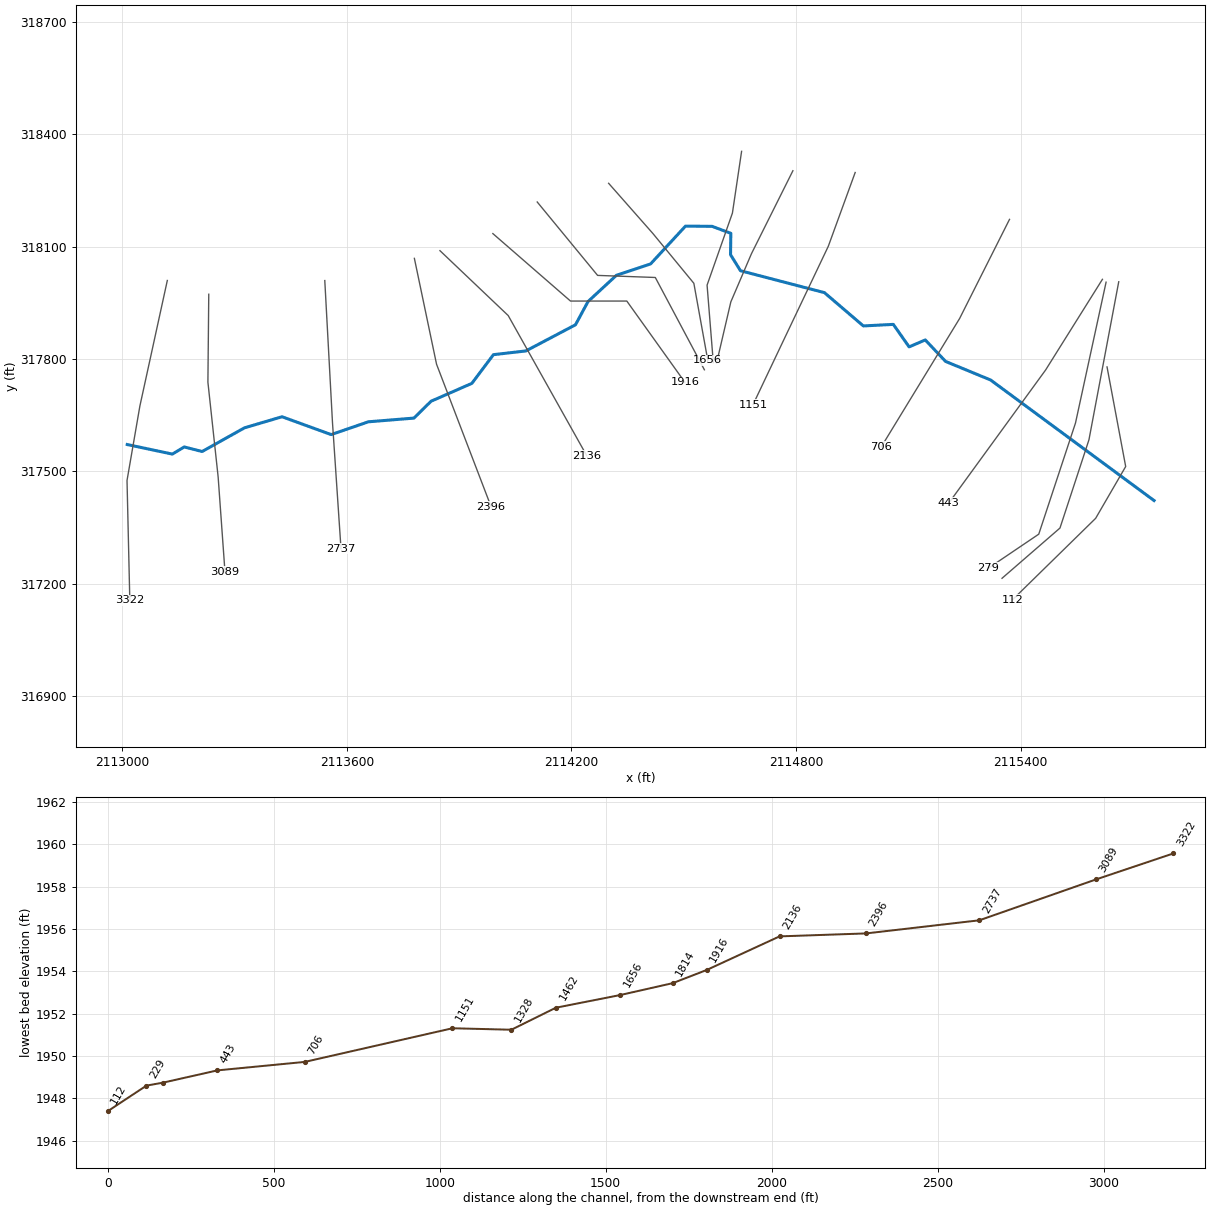
--- MLGNCKTR4.prj (project) ---

Proj Title=MLGNCKTR4
Current Plan=p01
Default Exp/Contr=0,0
English Units
Geom File=g01
Flow File=f01
Plan File=p01
BEGIN DESCRIPTION:
Stream Name- Milligan Creek Tributary 4
Flood Zone: Zone A
Greenbrier County, WV
County-Wide Study
WVDHSEM-2018-3, Flood Risk Project
HEC-RAS Version: 5.0.7
General Notes:
For the Hydrology Regression was used.
END DESCRIPTION:
DSS File=dss
DSS Export Rating Curves= 0
DSS Export Rating Curve Sorted= 0
DSS Export Volume Flow Curves= 0
DXF Filename=..\..\H1\MEADOWRV4\MEADOWRV4.
DXF OffsetX= 0
DXF OffsetY= 0
DXF ScaleX= 0
DXF ScaleY= 0

--- MLGNCKTR4.p01 (plan) ---

Plan Title=Floodplain
Program Version=5.07
Short Identifier=Floodplain
Geom File=g01
Flow File=f01
Subcritical Flow
K Sum by GR= 0
Std Step Tol= 0.01
Critical Tol= 0.01
Num of Std Step Trials= 20
Max Error Tol= 0.3
Flow Tol Ratio= 0.001
Split Flow NTrial= 30
Split Flow Tol= 0.02
Split Flow Ratio= 0.02
Log Output Level= 0
Friction Slope Method= 1
Unsteady Friction Slope Method= 2
Unsteady Bridges Friction Slope Method= 1
Parabolic Critical Depth
Global Vel Dist= 0 , 0 , 0
Global Log Level= 0
CheckData=True
Encroach Param=-1 ,0,0, 0
Computation Interval=0.1SEC
Output Interval=1MIN
Instantaneous Interval=Max Profile
Mapping Interval=1HOUR
Computation Time Step Use Courant=        0
Computation Time Step Use Time Series=    0
Computation Time Step Count To Double=0
Computation Time Step Max Doubling=0
Computation Time Step Max Halving=0
Computation Time Step Residence Courant=0
Run HTab= 0
Run UNet= 0
Run Sediment= 0
Run PostProcess= 0
Run WQNet= 0
Run RASMapper= 0
UNET Theta= 0
UNET Theta Warmup= 0
UNET ZTol= 0
UNET ZSATol= 0
UNET MxIter= 0
UNET Max Iter WO Improvement= 0
UNET MaxInSteps= 0
UNET DtIC= 0
UNET DtMin= 0
UNET MaxCRTS= 0
UNET WFStab= 0
UNET SFStab= 0
UNET WFX= 1
UNET SFX= 1
UNET 1D Methodology=Finite Difference
UNET DSS MLevel= 1
UNET Pardiso=0
UNET DZMax Abort= 0
UNET Use Existing IB Tables= 0
UNET Froude Reduction=False
UNET Froude Limit= 0
UNET Froude Power= 0
UNET D1 Cores= 0
UNET D2 Coriolis=0
UNET D2 Cores= 0
UNET D2 Theta= 1
UNET D2 Theta Warmup= 1
UNET D2 Z Tol= 0.01
UNET D2 Volume Tol= 0.01
UNET D2 Max Iterations= 20
UNET D2 Equation= 0
UNET D2 RampUpFraction=0.1
UNET D2 TimeSlices= 1
UNET D2 BCVolumeCheck=0
UNET D1D2 MaxIter= 0
UNET D1D2 ZTol=0.01
UNET D1D2 QTol=0.1
UNET D1D2 MinQTol=1
DSS File=dss
Write IC File= 0
Write IC File at Fixed DateTime=0
Write IC File at Sim End=0
Echo Input=False
Echo Parameters=False
Echo Output=False
Write Detailed= 0
HDF Write Warmup=0
HDF Write Time Slices=0
HDF Flush=0
HDF Face Node Velocities=0
HDF Compression= 1
HDF Chunk Size= 1
HDF Spatial Parts= 1
HDF Use Max Rows=0
HDF Fixed Rows= 1
Calibration Method= 0
Calibration Iterations= 20
Calibration Max Change=0.05
Calibration Tolerance=0.2
Calibration Maximum=1.5
Calibration Minimum=0.5
Calibration Optimization Method= 1
WQ AD Non Conservative
WQ ULTIMATE=-1
WQ Max Comp Step=1HOUR
WQ Output Interval=15MIN
WQ Output Selected Increments= 0
WQ Output face flow=0
WQ Output face velocity=0
WQ Output face area=0
WQ Output face dispersion=0
WQ Output cell volume=0
WQ Output cell surface area=0
WQ Output cell continuity=0
WQ Output cumulative cell continuity=0
WQ Output face conc=0
WQ Output face dconc_dx=0
WQ Output face courant=0
WQ Output face peclet=0
WQ Output face adv mass=0
WQ Output face disp mass=0
WQ Output cell mass=0
WQ Output cell source sink temp=0
WQ Output nsm pathways=0
WQ Output nsm derived pathways=0
WQ Output MaxMinRange=-1
WQ Daily Max Min Mean=-1
WQ Daily Range=0
WQ Daily Time=0
WQ Create Restart=0
WQ Fixed Restart=0
WQ System Summary=0
WQ Write To DSS=0
WQ Use Fixed Temperature=0
Sorting and Armoring Iterations= 10
XS Update Threshold= 0.02
Bed Roughness Predictor= 0
Hydraulics Update Threshold= 0.02
Energy Slope Method= 1
Volume Change Method= 1
Sediment Retention Method= 0
XS Weighting Method= 0
Number of US Weighted Cross Sections= 1
Number of DS Weighted Cross Sections= 1
Upstream XS Weight=0
Main XS Weight=1
Downstream XS Weight=0
Number of DS XS's Weighted with US Boundary= 1
Upstream Boundary Weight= 1
Weight of XSs Associated with US Boundary= 0
Number of US XS's Weighted with DS Boundary= 1
Downstream Boundary Weight= 0.5
Weight of XSs Associated with DS Boundary= 0.5
Percentile Method= 0
Sediment Output Level= 3
Mass or Volume Output= 0
Output Increment Type= 1
Profile and TS Output Increment= 1
XS Output Flag= 0
XS Output Increment= 10
Write Gradation File= 0
Read Gradation Hotstart= 0
Write HDF5 File= 1
Write Binary Output= 1
Write DSS Sediment File= 0
SV Curve= 0
Specific Gage Flag= 0

--- MLGNCKTR4.f01 (steady flow) ---

Flow Title=MasterFlow
Program Version=5.07
Number of Profiles= 6
Profile Names=f1p,f10p,f4p,f2p,f02p,f1pplus
River Rch & RM=MLGNCKTR4,Main            ,3322
     500     263     350     423     700     739
River Rch & RM=MLGNCKTR4,Main            ,2737
     557     294     391     471     778     823
Boundary for River Rch & Prof#=MLGNCKTR4,Main            , 1
Up Type= 0
Dn Type= 3
Dn Slope=0.01016
Boundary for River Rch & Prof#=MLGNCKTR4,Main            , 2
Up Type= 0
Dn Type= 3
Dn Slope=0.01016
Boundary for River Rch & Prof#=MLGNCKTR4,Main            , 3
Up Type= 0
Dn Type= 3
Dn Slope=0.01016
Boundary for River Rch & Prof#=MLGNCKTR4,Main            , 4
Up Type= 0
Dn Type= 3
Dn Slope=0.01016
Boundary for River Rch & Prof#=MLGNCKTR4,Main            , 5
Up Type= 0
Dn Type= 3
Dn Slope=0.01016
Boundary for River Rch & Prof#=MLGNCKTR4,Main            , 6
Up Type= 0
Dn Type= 3
Dn Slope=0.01016
DSS Import GetInterval= 0
DSS Import GetPeak= 0
DSS Import FillOption= 0

--- MLGNCKTR4.g01 (geometry) ---

Geom Title=MasterGeometry
Program Version=5.07

River Reach=MLGNCKTR4       ,Main
Reach XY= 30
     2113013.744       317571.59     2113134.226      317546.091
      2113166.03      317565.144     2113213.801      317552.978
     2113326.875      317616.176     2113427.252      317645.755
     2113558.416      317598.133      2113657.76      317632.287
      2113779.55      317642.145     2113825.092      317687.096
     2113934.131      317734.834      2113991.76      317811.405
     2114078.446      317821.382     2114210.881       317891.12
     2114244.201      317952.992     2114320.236      318023.204
     2114411.444      318053.506     2114504.651      318154.431
     2114575.828      318153.787     2114625.744       318135.19
     2114624.987      318078.153      2114651.54      318035.361
     2114875.705      317976.932     2114979.574      317888.075
     2115059.721      317892.209     2115101.909      317832.194
     2115145.021      317850.714     2115199.414      317793.309
     2115319.545      317743.811       2115756.1      317422.111

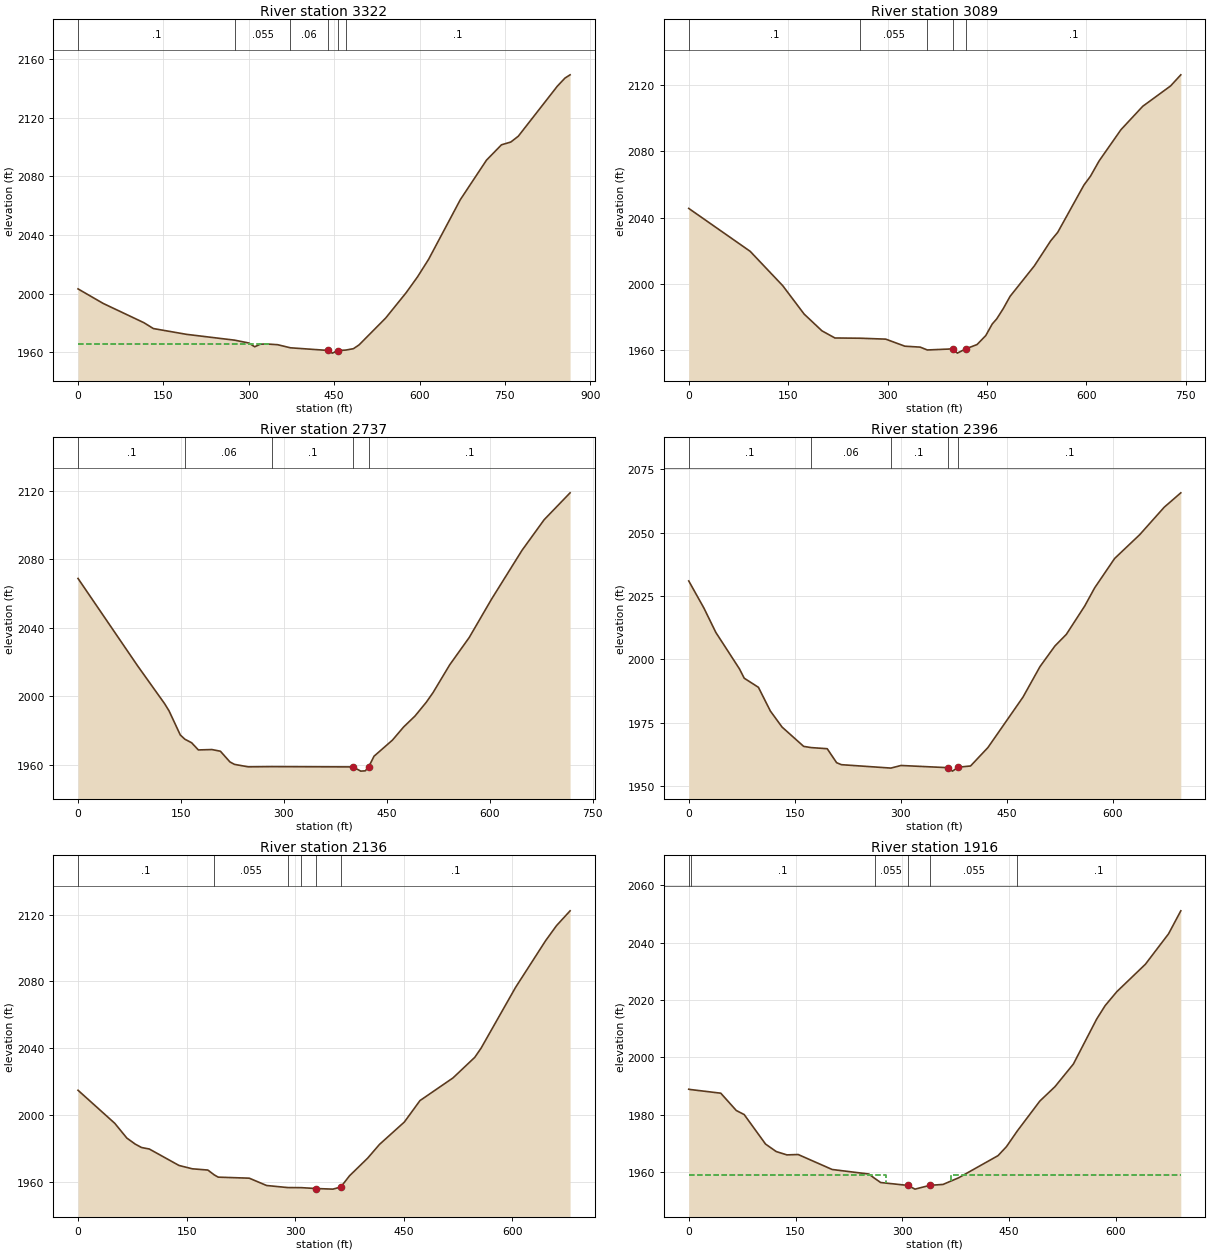
Type RM Length L Ch R = 1 ,3322    ,233.3,233.3,233.3
XS GIS Cut Line= 4
2113120.79242814318009.3788266732113047.53908446317674.506398451
2113013.15486192317475.6758941942113020.62969291317155.753127947
#Sta/Elev= 30
       0 2003.33    44.3  1993.4   115.7 1980.31   132.4 1976.31   190.3 1972.38
  275.56 1968.38   300.4 1966.43   310.4  1963.9   320.5 1965.66   330.9 1965.81
   350.7 1965.31  373.211963.199   438.4 1961.42   446.9 1959.57   457.2 1961.33
  470.73 1961.66   483.9 1962.59   493.8 1965.18   540.5 1983.44   576.5 2000.72
   596.3  2011.4     616 2023.47   671.8 2064.16   717.7 2091.02     744 2101.47
   760.4 2103.36   773.5 2107.29   842.4 2141.51   855.6 2146.92864.5826 2149.14
#Mann= 6 ,-1 , 0
       0      .1       0  275.56    .055       0  373.21     .06       0
   438.4    .045       0   457.2     .06       0  470.73      .1       0
#XS Ineff= 2 , 0
          335.03 1965.84
Permanent Ineff=
       F       F
Bank Sta=438.4,457.2
XS Rating Curve= 0 ,0
Exp/Cntr(USF)=0,0
Exp/Cntr=0.3,0.1

Type RM Length L Ch R = 1 ,3089    ,351.3,351.3,351.3
XS GIS Cut Line= 4
2113231.46367519317972.6743418572113229.18511064317737.982193809
2113256.52788517317485.0615294082113274.75640152317232.140865007
#Sta/Elev= 30
       0 2045.59    92.7 2019.73   141.9 1998.98   174.2 1981.87     201  1971.8
   220.6 1967.47  259.131967.324   297.4 1966.77   326.2 1962.52   349.3 1961.96
   360.11960.242   398.6  1960.9   405.4 1958.34  418.12 1960.92   435.1  1963.5
   448.3 1968.92   458.1 1975.93   464.8 1978.97   474.7 1985.19     485 1992.57
   521.7 2010.99   546.2 2025.99   556.9 2031.17   596.4 2059.64   606.3 2064.99
   619.4 2074.24   652.3 2093.04   685.2 2107.15   727.3 2119.45742.6743 2126.13
#Mann= 5 ,-1 , 0
       0      .1       0  259.13    .055       0   360.1      .1       0
   398.6    .045       0  418.12      .1       0
Bank Sta=398.6,418.12
XS Rating Curve= 0 ,0
Exp/Cntr(USF)=0,0
Exp/Cntr=0.3,0.1

Type RM Length L Ch R = 1 ,2737    ,341.1,341.1,341.1
XS GIS Cut Line= 3
2113541.34845319318009.1313745632113561.85553409317630.889660234
2113584.64117953317293.662107699
#Sta/Elev= 30
       0  2068.8    86.6 2017.95     126 1995.84   132.6 1991.56     149 1977.49
  155.681975.017   165.5 1972.96   175.3 1968.77     195    1969   207.4 1968.02
   221.3 1961.78   227.9 1960.35   247.9 1958.91  282.23 1959.03   400.4 1958.87
   411.9 1956.41   418.5 1956.58  423.661959.099   431.2 1965.11     458 1974.49
   474.3 1982.16   490.8 1988.52   507.3 1996.58   517.2 2002.25   541.5 2018.46
   569.8 2034.32   602.6 2056.88   646.8 2085.23     679 2103.06716.7937 2118.75
#Mann= 5 ,-1 , 0
       0      .1       0  155.68     .06       0  282.23      .1       0
   400.4    .045       0  423.66      .1       0
Bank Sta=400.4,423.66
XS Rating Curve= 0 ,0
Exp/Cntr(USF)=0,0
Exp/Cntr=0.3,0.1

Type RM Length L Ch R = 1 ,2396    ,260.5,260.5,260.5
XS GIS Cut Line= 3
2113780.59773033318068.3740527112113839.84040847317785.832049236
 2113985.6685393317405.311770363
#Sta/Elev= 30
       0 2030.95    21.5 2020.22    38.3 2010.62    71.8 1996.18    78.5 1992.51
    98.6 1988.91   115.5 1979.54   132.1 1973.19   162.6 1965.57  173.091965.092
   195.9 1964.65   209.2 1959.13   215.9 1958.34  286.041956.992   300.3 1958.02
   366.2 1957.16   373.1 1955.79   381.4 1957.35   398.7 1957.82   423.3 1965.11
   472.9 1985.04     497 1997.11   518.1 2005.25   534.2 2009.82   560.3 2021.07
   574.3 2028.21   602.5 2039.81     638 2049.22   672.7 2060.08696.1926 2065.77
#Mann= 5 ,-1 , 0
       0      .1       0  173.09     .06       0  286.04      .1       0
   366.2    .045       0   381.4      .1       0
Bank Sta=366.2,381.4
XS Rating Curve= 0 ,0
Exp/Cntr(USF)=0,0
Exp/Cntr=0.3,0.1

Type RM Length L Ch R = 1 ,2136    ,219.8,219.8,219.8
XS GIS Cut Line= 3
2113848.95466665318088.8811336092114031.23983018317915.710228253
2114240.86776825317542.025643012
#Sta/Elev= 30
       0 2014.82    50.8 1995.03    67.5 1986.19    79.1 1982.57    87.9 1980.54
    98.5 1979.66   139.5 1969.82     158 1967.81   179.4 1967.06  188.331964.146
   193.7 1962.82   236.6  1962.2   260.5 1957.83  289.791956.581  308.59 1956.53
   328.7 1956.01   352.1 1955.65  363.04  1956.9   375.1 1963.61   400.3 1974.23
   416.5 1982.39   450.9 1995.81   472.5 2008.64   518.1  2022.2   548.2 2034.52
   556.9    2040   604.6 2076.41     646 2104.28     661 2113.27   679.9  2122.2
#Mann= 6 ,-1 , 0
       0      .1       0  188.33    .055       0  289.79     .06       0
  308.59      .1       0   328.7    .045       0  363.04      .1       0
Bank Sta=328.7,363.04
XS Rating Curve= 0 ,0
Exp/Cntr(USF)=0,0
Exp/Cntr=0.5,0.3

Type RM Length L Ch R = 1 ,1916    ,102.1,102.1,102.1
XS GIS Cut Line= 4
2113990.22566839318134.4524244922114197.57504191317954.445825504
2114347.96030182317954.4458255042114502.90269082317737.982193809
#Sta/Elev= 30
       0 1988.87    2.611988.758      45 1987.49    66.8 1981.46    77.9 1980.04
   107.9 1969.76   122.9 1967.15   137.9 1965.99   153.7 1966.12   201.5  1960.9
     253 1959.32  261.13 1957.82   269.6 1956.36   307.9 1955.35   317.8 1954.06
   338.5 1955.37   357.2  1955.7   379.1 1958.01   434.4 1965.72   446.2 1968.84
  461.481974.324   493.2 1984.76   514.4 1989.76   540.3 1997.66     573 2013.33
   584.9 2018.01   601.3 2022.87   641.4 2032.42   673.9 2043.01691.1711 2051.04
#Mann= 6 ,-1 , 0
       0      .1       0    2.61      .1       0  261.13    .055       0
   307.9    .045       0   338.5    .055       0  461.48      .1       0
#XS Ineff= 2 , 0
             277 1959.06     368         1959.06
Permanent Ineff=
       F       F
Bank Sta=307.9,338.5
XS Rating Curve= 0 ,0
Exp/Cntr(USF)=0,0
Exp/Cntr=0.5,0.3

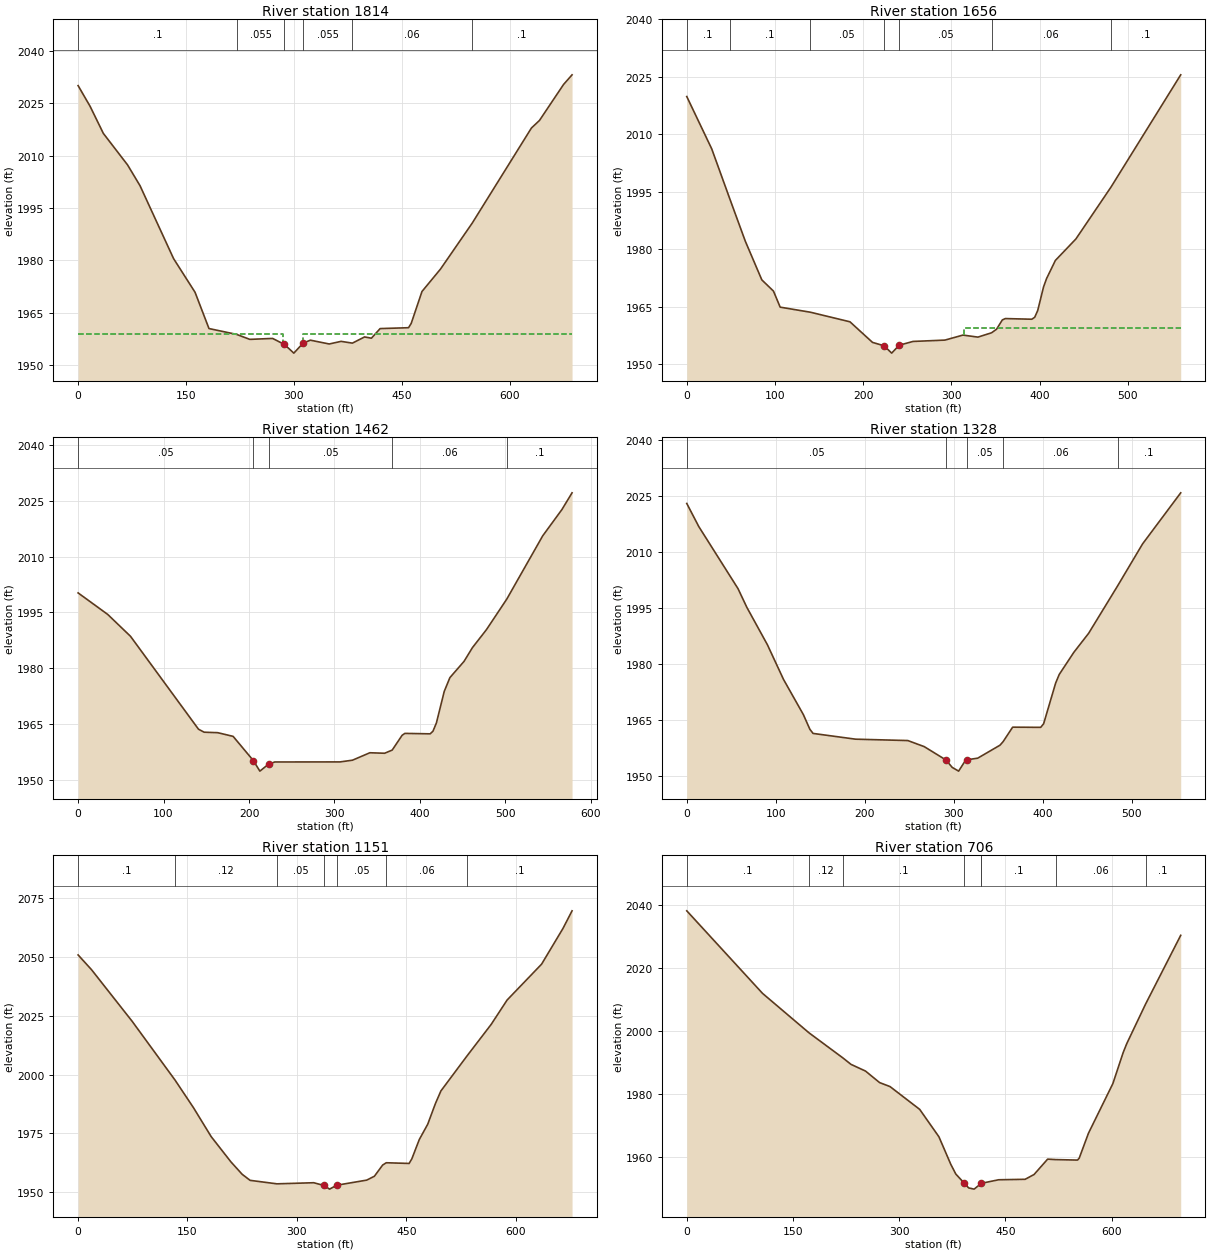
Type RM Length L Ch R = 1 ,1814    ,157.6,157.6,157.6
XS GIS Cut Line= 4
2114108.71102468318218.7593126252114269.94239226318022.915453315
2114424.07274046318017.3540489982114555.16298506317771.063286412
#Sta/Elev= 30
       0 2030.07    16.8 2024.09    35.1 2016.38    68.8 2007.35    86.1  2001.4
   132.8  1980.5   162.6 1970.88     182 1960.48  220.331958.811   238.8 1957.38
   270.5 1957.65   286.9 1955.93     300 1953.44   312.8 1956.29     323 1957.15
   349.2 1956.06   365.7 1956.81  381.421956.304   398.4 1958.08   407.9 1957.72
     420 1960.47   459.5 1960.72   463.2 1961.94   478.2 1971.09     504 1977.53
  548.06 1990.68   630.4 2017.92   641.6 2020.09     675 2030.37686.9094 2033.16
#Mann= 6 ,-1 , 0
       0      .1       0  220.33    .055       0   286.9    .045       0
   312.8    .055       0  381.42     .06       0  548.06      .1       0
#XS Ineff= 2 , 0
             285 1959.06     313         1959.06
Permanent Ineff=
       F       F
Bank Sta=286.9,312.8
XS Rating Curve= 0 ,0
Exp/Cntr(USF)=0,0
Exp/Cntr=0.5,0.3

Type RM Length L Ch R = 1 ,1656    ,194.1,194.1,194.1
XS GIS Cut Line= 4
2114299.45608818318268.6373244542114417.15776683318135.242088645
2114527.01266691318001.8468528352114564.28486515317795.868915189
#Sta/Elev= 30
       0 2019.86    28.3  2006.2   48.691993.223    66.4 1982.08    85.1    1972
    98.3 1969.07   105.9 1964.88  140.181963.559     185 1961.06   210.6 1955.68
   223.8 1954.79   232.3 1952.88   240.8 1954.94   256.5 1955.93   292.7 1956.28
   313.1 1957.59   330.1 1957.06  345.591958.193   351.2 1959.12   357.8 1961.55
   361.2  1961.9   391.2 1961.73   394.5 1962.24   397.9 1964.01   404.5 1970.16
   407.9 1972.33   417.9 1977.07   441.2 1982.69  480.991996.228560.0292 2025.53
#Mann= 7 ,-1 , 0
       0      .1       0   48.69      .1       0  140.18     .05       0
   223.8    .045       0   240.8     .05       0  345.59     .06       0
  480.99      .1       0
#XS Ineff= 2 , 0
                          314.81         1959.37
Permanent Ineff=
       F       F
Bank Sta=223.8,240.8
XS Rating Curve= 0 ,0
Exp/Cntr(USF)=0,0
Exp/Cntr=0.3,0.1

Type RM Length L Ch R = 1 ,1462    ,134,134,134
XS GIS Cut Line= 4
2114654.52281879318353.9710414792114630.00163574318189.188691362
2114562.32317051317996.9426162252114578.99757499317789.983831256
#Sta/Elev= 30
       0 2000.22    34.7 1994.42    61.3 1988.55   140.9 1963.55   147.5 1962.75
   163.4 1962.62   181.4 1961.63  205.061955.122   212.7 1952.28   222.9 1954.16
   230.1 1954.74   306.6 1954.76   321.1 1955.22   341.4 1957.22   358.7 1957.09
  367.551957.939   379.1  1961.9   382.4 1962.43     412 1962.31   415.3 1963.03
   419.3 1965.25   428.5 1973.75   435.1 1977.44   451.6 1981.79   461.4 1985.48
   477.9 1990.35  501.63 1998.55   543.7 2015.57   566.1 2022.62578.0373 2027.14
#Mann= 5 ,-1 , 0
       0     .05       0  205.06    .045       0   222.9     .05       0
  367.55     .06       0  501.63      .1       0
Bank Sta=205.06,222.9
XS Rating Curve= 0 ,0
Exp/Cntr(USF)=0,0
Exp/Cntr=0.3,0.1

Type RM Length L Ch R = 1 ,1328    ,177.4,177.4,177.4
XS GIS Cut Line= 4
2114791.53882956318302.2028229252114681.02862566318081.182415128
2114625.77352371317952.253843913   2114587.72836317789.138941122
#Sta/Elev= 30
       0 2023.03    13.5 2016.83    57.6 2000.17    67.4 1995.21    90.6 1985.13
   108.7 1975.83     131 1966.39   138.3 1962.46   141.9 1961.35   189.6 1959.81
   248.3 1959.44   266.7 1957.82   291.1 1954.24   298.2 1952.24   305.4 1951.24
   312.5 1953.89   315.3 1954.31   326.8 1954.71   351.8 1958.18   355.3 1959.12
   366.1 1963.03   397.6 1962.98   400.9 1963.95   414.4 1974.86   418.4 1977.16
   434.8 1983.09   451.5 1988.22     484 2000.92   512.1  2012.2   554.9 2025.88
#Mann= 5 ,-1 , 0
       0     .05       0   291.1    .045       0   315.3     .05       0
   355.3     .06       0     484      .1       0
Bank Sta=291.1,315.3
XS Rating Curve= 0 ,0
Exp/Cntr(USF)=0,0
Exp/Cntr=0.3,0.1

Type RM Length L Ch R = 1 ,1151    ,444.9,444.9,444.9
XS GIS Cut Line= 4
2114957.85808629 318297.504871542114886.08330315318100.636894925
2114763.04081776317842.2476756182114685.11391035317678.191028439
#Sta/Elev= 30
       0 2050.89    18.4 2044.62    74.2 2022.64  132.961997.658     158 1986.04
   182.5 1973.63   209.5 1962.92     225 1957.61   235.9 1955.04  272.68 1953.56
   323.1 1954.03   336.9 1952.88   344.9 1951.31   354.6 1952.97   395.8 1955.14
   406.3 1956.79   417.6 1961.54  422.611962.526   453.9 1962.23   457.6 1964.15
   467.9 1972.42   479.4 1978.89     490  1987.7   497.5 1993.06  533.172007.885
   566.4 2021.34   588.3 2031.72   635.6 2046.98   664.9 2062.16677.3571 2069.65
#Mann= 7 ,-1 , 0
       0      .1       0  132.96     .12       0  272.68     .05       0
   336.9    .045       0   354.6     .05       0  422.61     .06       0
  533.17      .1       0
Bank Sta=336.9,354.6
XS Rating Curve= 0 ,0
Exp/Cntr(USF)=0,0
Exp/Cntr=0.3,0.1

Type RM Length L Ch R = 1 ,706     ,263,263,263
XS GIS Cut Line= 3
2115370.05041233318172.4116780662115236.75438649317907.870334489
2115027.58216134317565.402083503
#Sta/Elev= 30
       0 2038.07     107 2011.86  172.541999.352  220.341991.392   231.9 1989.33
   252.4  1987.2   272.3 1983.54     287 1982.28   328.9 1975.04   356.1 1966.33
   372.8 1957.61   379.9 1954.52   391.9 1951.59   398.1  1950.1   405.8 1949.72
   415.7 1951.52  415.941951.564   440.4 1952.69   477.8 1952.84   490.4 1954.36
   509.6 1959.24  521.531959.092   551.8 1958.94   554.2 1959.56   567.2 1967.44
   601.7 1983.22   616.2 1993.04   621.4 1995.95  647.972008.496 697.521 2030.29
#Mann= 8 ,-1 , 0
       0      .1       0  172.54     .12       0  220.34      .1       0
   391.9    .045       0   415.7      .1       0  415.94      .1       0
  521.53     .06       0  647.97      .1       0
Bank Sta=391.9,415.7
XS Rating Curve= 0 ,0
Exp/Cntr(USF)=0,0
Exp/Cntr=0.3,0.1

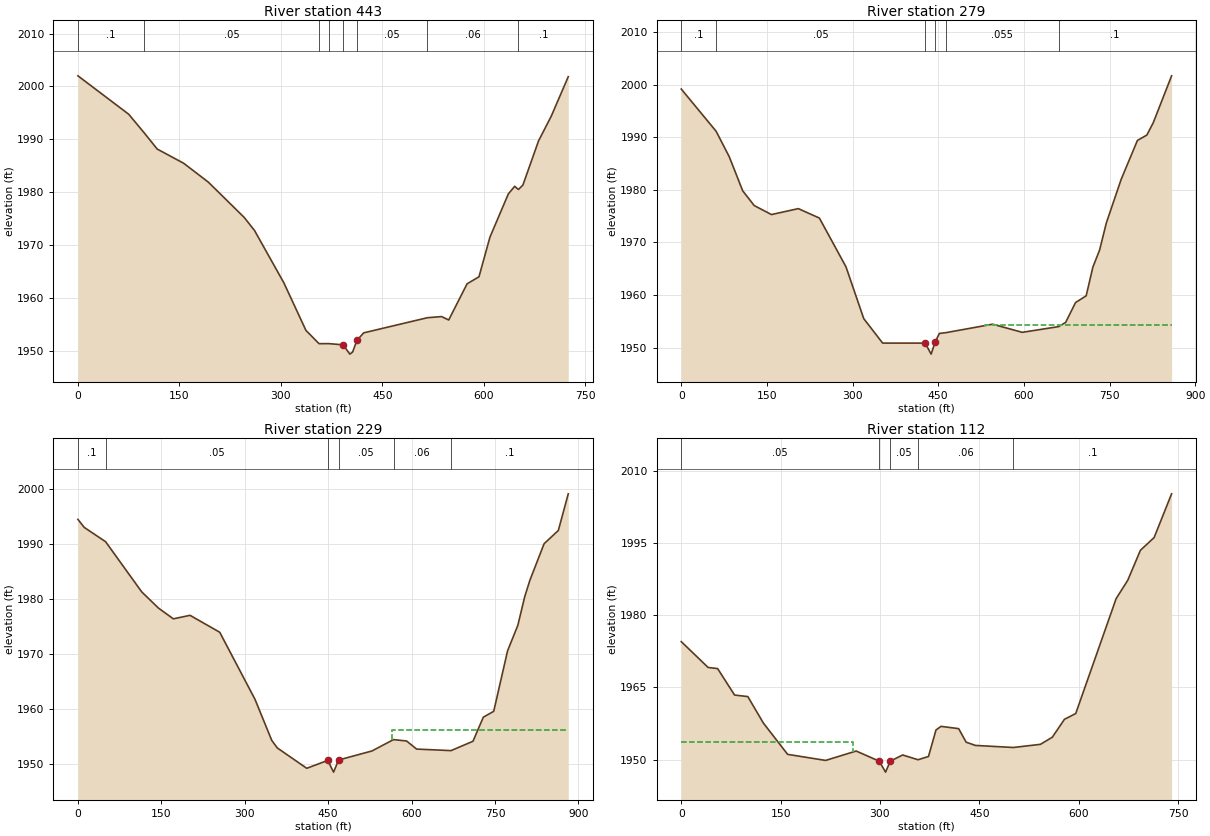
Type RM Length L Ch R = 1 ,443     ,163.9,163.9,163.9
XS GIS Cut Line= 3
2115618.18609118318012.4564470662115466.43369254317770.472892477
2115208.04447324317415.700392952
#Sta/Elev= 30
       0 2002.02      75 1994.75   97.471991.296   117.1 1988.16   156.4 1985.45
   192.6  1981.9   245.6 1975.22   260.9 1972.74   304.4  1962.8   336.9 1953.82
  356.281951.298  370.51 1951.31   391.8 1951.08   401.8 1949.32   405.9 1949.72
  412.261951.924   422.3 1953.35  516.351956.215   537.4 1956.43   547.9 1955.79
     575 1962.63   592.6 1963.97   608.8 1971.47     636 1979.66   645.4  1981.1
  650.841980.496   657.5 1981.33   680.6 1989.69   699.4 1994.38724.5252 2001.85
#Mann= 8 ,-1 , 0
       0      .1       0   97.47     .05       0  356.28      .1       0
  370.51     .05       0   391.8    .045       0  412.26     .05       0
  516.35     .06       0  650.84      .1       0
Bank Sta=391.8,412.26
XS Rating Curve= 0 ,0
Exp/Cntr(USF)=0,0
Exp/Cntr=0.5,0.3

Type RM Length L Ch R = 1 ,279     ,49.8,49.8,49.8
XS GIS Cut Line= 4
2115627.96209279318004.8513980822115546.22481594  317628.8599246
2115448.14008373317332.4260672462115314.09094971317241.970147539
#Sta/Elev= 30
       0 1999.22   61.06 1991.18    84.1 1986.32   107.6 1979.84   127.8 1977.03
     158 1975.32     205 1976.45   241.9 1974.65   288.5 1965.36   319.6  1955.5
   352.7 1950.84   427.2 1950.84   437.6 1948.74  444.691951.063     452 1952.68
   463.41952.827   545.3 1954.44   597.2 1952.89  661.111953.984   673.2 1954.79
   690.5 1958.56   709.1 1959.84   720.9 1965.32   732.7 1968.58   744.5 1973.75
   770.5 1982.05   798.9 1989.44   815.4 1990.46   826.7 1992.83858.7272 2001.74
#Mann= 6 ,-1 , 0
       0      .1       0   61.06     .05       0   427.2    .045       0
  444.69     .05       0   463.4    .055       0  661.11      .1       0
#XS Ineff= 2 , 0
                           531.6         1954.35
Permanent Ineff=
       F       F
Bank Sta=427.2,444.69
XS Rating Curve= 0 ,0
Exp/Cntr(USF)=0,0
Exp/Cntr=0.5,0.3

Type RM Length L Ch R = 1 ,229     ,116.9,116.9,116.9
XS GIS Cut Line= 4
2115661.74683388 318005.941228442115582.18921775317584.176879925
2115504.81126234317348.7735226152115350.05535152317214.724388591
#Sta/Elev= 30
       0 1994.55    11.3  1993.1    49.81990.492   114.8 1981.36   144.9 1978.42
   171.6 1976.47   201.6 1977.11     255 1974.03   318.5 1961.82   348.5 1954.38
   358.5    1953   411.5  1949.3   449.2 1950.73   459.7  1948.6  468.791950.807
   528.8 1952.45  567.491954.512     591 1954.26   609.1 1952.79  670.87 1952.51
   710.4 1954.21     729 1958.59   747.7 1959.66   772.6 1970.65   791.1  1975.3
   803.4 1980.48   812.7 1983.47   838.3 1990.13   863.9 1992.54881.7369  1999.2
#Mann= 6 ,-1 , 0
       0      .1       0    49.8     .05       0   449.2    .045       0
  468.79     .05       0  567.49     .06       0  670.87      .1       0
#XS Ineff= 2 , 0
                           564.5         1956.22
Permanent Ineff=
       F       F
Bank Sta=449.2,468.79
XS Rating Curve= 0 ,0
Exp/Cntr(USF)=0,0
Exp/Cntr=0.5,0.3

Type RM Length L Ch R = 1 ,112     ,112,112,112
XS GIS Cut Line= 4
2115630.49033972317778.6757248362115680.31863301317512.911782991
2115600.07551359 317374.671161412115378.41382726317157.776393068
#Sta/Elev= 30
       0 1974.48    40.5 1969.12    54.9 1968.88    80.5 1963.39   100.5 1963.07
   123.9 1957.59   160.6 1951.08   217.9 1949.82   264.1 1951.77  298.881949.664
   308.5 1947.39  315.551949.665   334.3 1950.95  357.491949.961   373.3 1950.64
   384.6 1956.14   392.2 1956.89   418.8 1956.42   430.2  1953.6   444.2 1952.93
  501.511952.507   542.3 1953.16   560.2 1954.63   578.6 1958.36   595.6 1959.55
   656.6  1983.4   674.1  1987.2   693.3 1993.44     714 1996.09740.3612 2005.16
#Mann= 5 ,-1 , 0
       0     .05       0  298.88    .045       0  315.55     .05       0
  357.49     .06       0  501.51      .1       0
#XS Ineff= 2 , 0
          259.74 1953.72
Permanent Ineff=
       F       F
Bank Sta=298.88,315.55
XS Rating Curve= 0 ,0
Exp/Cntr(USF)=0,0
Exp/Cntr=0.3,0.1
Stream Node=BIGCLEARCK      ,Main            , 0 , 0 ,Upstream end
Stream Node=BIGCLEARCK      ,Main            , 0 , 1 ,Downstream end
Stream Node=BROADRN         ,Main            , 0 , 0 ,Upstream end
Stream Node=BROADRN         ,Main            , 0 , 1 ,Downstream end
Stream Node=LAURELBR        ,Main            , 0 , 0 ,Upstream end
Stream Node=LAURELBR        ,Main            , 0 , 1 ,Downstream end
Stream Node=LAURELCK1       ,Main            , 0 , 0 ,Upstream end
Stream Node=LAURELCK1       ,Main            , 0 , 1 ,Downstream end
Stream Node=MEADOWRV3       ,Main            , 0 , 0 ,Upstream end
Stream Node=MEADOWRV3       ,Main            , 0 , 1 ,Downstream end
Stream Node=MEADOWRV4       ,Main            , 0 , 0 ,Upstream end
Stream Node=MEADOWRV4       ,Main            , 0 , 1 ,Downstream end
Stream Node=MLGNCK          ,Main            , 0 , 0 ,Upstream end
Stream Node=MLGNCK          ,Main            , 0 , 1 ,Downstream end
Stream Node=MLGNCKTR3       ,Main            , 0 , 0 ,Upstream end
Stream Node=MLGNCKTR3       ,Main            , 0 , 1 ,Downstream end
Stream Node=MLGNCKTR4       ,Main            , 0 , 0 ,Upstream end
Stream Node=MLGNCKTR4       ,Main            , 0 , 1 ,Downstream end
Stream Node=MUDDYCK         ,Main            , 0 , 0 ,Upstream end
Stream Node=MUDDYCK         ,Main            , 0 , 1 ,Downstream end
Stream Node=SECONDCK        ,Main            , 0 , 0 ,Upstream end
Stream Node=SECONDCK        ,Main            , 0 , 1 ,Downstream end
Stream Node=TUCKHORN        ,Main            , 0 , 0 ,Upstream end
Stream Node=TUCKHORN        ,Main            , 0 , 1 ,Downstream end
Stream Node=TUCKHORNT2      ,Main            , 0 , 0 ,Upstream end
Stream Node=TUCKHORNT2      ,Main            , 0 , 1 ,Downstream end
LCMann Table=0

Chan Stop Cuts=-1
Use User Specified Reach Order=0
Composite Channel Slope=5